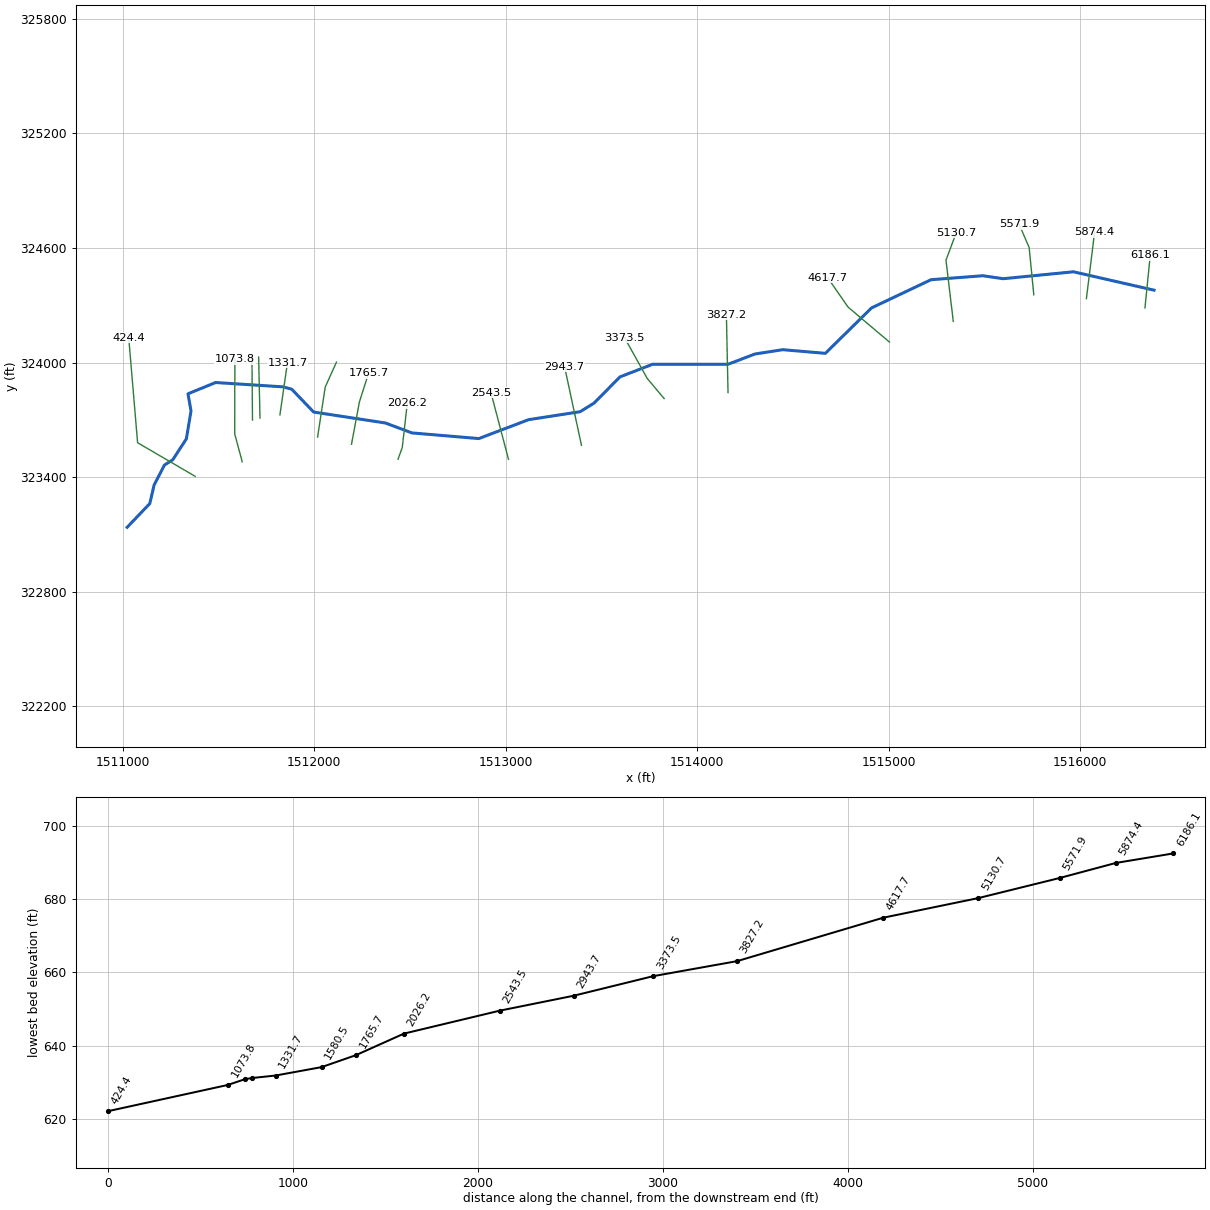
--- ShawneeRn.prj (project) ---

Proj Title=ShawneeRn
Current Plan=p01
Default Exp/Contr=0,0
English Units
Geom File=g01
Flow File=f01
Plan File=p01
BEGIN DESCRIPTION:
AMEC Environment & Infrastructure, 2013
Projection: NAD 1983 State Plane West Virginia North FIPS 4701 (US Feet)
Vertical Datum: NAVD 1988
END DESCRIPTION:
DSS Export Rating Curves= 0
DSS Export Rating Curve Sorted= 0
DSS Export Volume Flow Curves= 0
DXF OffsetX= 0
DXF OffsetY= 0
DXF ScaleX= 0
DXF ScaleY= 0

--- ShawneeRn.p01 (plan) ---

Plan Title=Floodplain
Program Version=4.00
Geom File=g01
Flow File=f01
K Sum by GR=0
Std Step Tol=0.01
Critical Tol=0.01
Num of Std Step Trials=20
Max Error Tol=0.3
Flow Tol Ratio=0.001
Split Flow NTrial=30
Split Flow Tol=0.02
Split Flow Ratio=0.02
Log Output Level=0
Friction Slope Method=1
Unsteady Friction Slope Method=2
Unsteady Bridges Friction Slope Method=1
Global Log Level=0
CheckData=False
Run HTab=0
Run UNet=0
Run PostProcess=0
UNET Theta=0
UNET Theta Warmup=0
UNET ZTol=0
UNET ZSATol=0
UNET MxIter=0
UNET MaxInSteps=0
UNET DtIC=0
UNET DtMin=0
UNET MaxCRTS=0
UNET WFStab=0
UNET SFStab=0
UNET WFX=0
UNET SFX=0
UNET DSS MLevel=0
UNET DZMax Abort=0
UNET Convert EG Bridges=0
UNET Use Existing IB Tables=0
UNET Froude Limit=0
UNET Froude Power=0
Write IC File=0
Echo Input=False
Echo Output=False
Write Detailed=0

--- ShawneeRn.f01 (steady flow) ---

Flow Title=USGS Regress. Eqn. (2010) - Western-Plateaus
Program Version=4.10
Number of Profiles= 1
Profile Names=P100yr
River Rch & RM=ShawneeRn,Main            ,6186.1
     841
River Rch & RM=ShawneeRn,Main            ,5130.7
     919
River Rch & RM=ShawneeRn,Main            ,4617.7
     981
River Rch & RM=ShawneeRn,Main            ,2543.5
    1055
River Rch & RM=ShawneeRn,Main            ,424.4
    1104
Boundary for River Rch & Prof#=ShawneeRn,Main            , 1
Up Type= 0
Dn Type= 3
Dn Slope=0.012201
DSS Import GetInterval= 0
DSS Import GetPeak= 0
DSS Import FillOption= 0

--- ShawneeRn.g01 (geometry) ---

Geom Title=USGS 3m DEM
Program Version=4.10

River Reach=ShawneeRn       ,Main
Reach XY= 30
     1516387.407      324378.717     1515966.295      324475.013
     1515598.883      324438.732      1515492.98      324454.357
     1515222.146      324433.524     1514911.383      324285.954
     1514670.063      324048.107     1514447.841      324067.204
     1514302.008      324044.635     1514161.383      323990.815
     1513767.285      323990.815     1513597.146      323924.843
      1513461.73       323787.69     1513388.813      323742.551
     1513119.716      323700.885     1512859.299      323601.926
     1512510.341       323631.44     1512371.452      323683.524
     1511996.452      323740.815     1511881.869      323860.607
     1511834.994       323872.76     1511484.299      323895.329
     1511340.202      323836.301     1511355.827      323746.024
     1511331.521       323600.19     1511260.341      323490.815
     1511216.938      323463.037     1511163.119      323358.871
     1511140.549      323261.649     1511022.144      323137.558

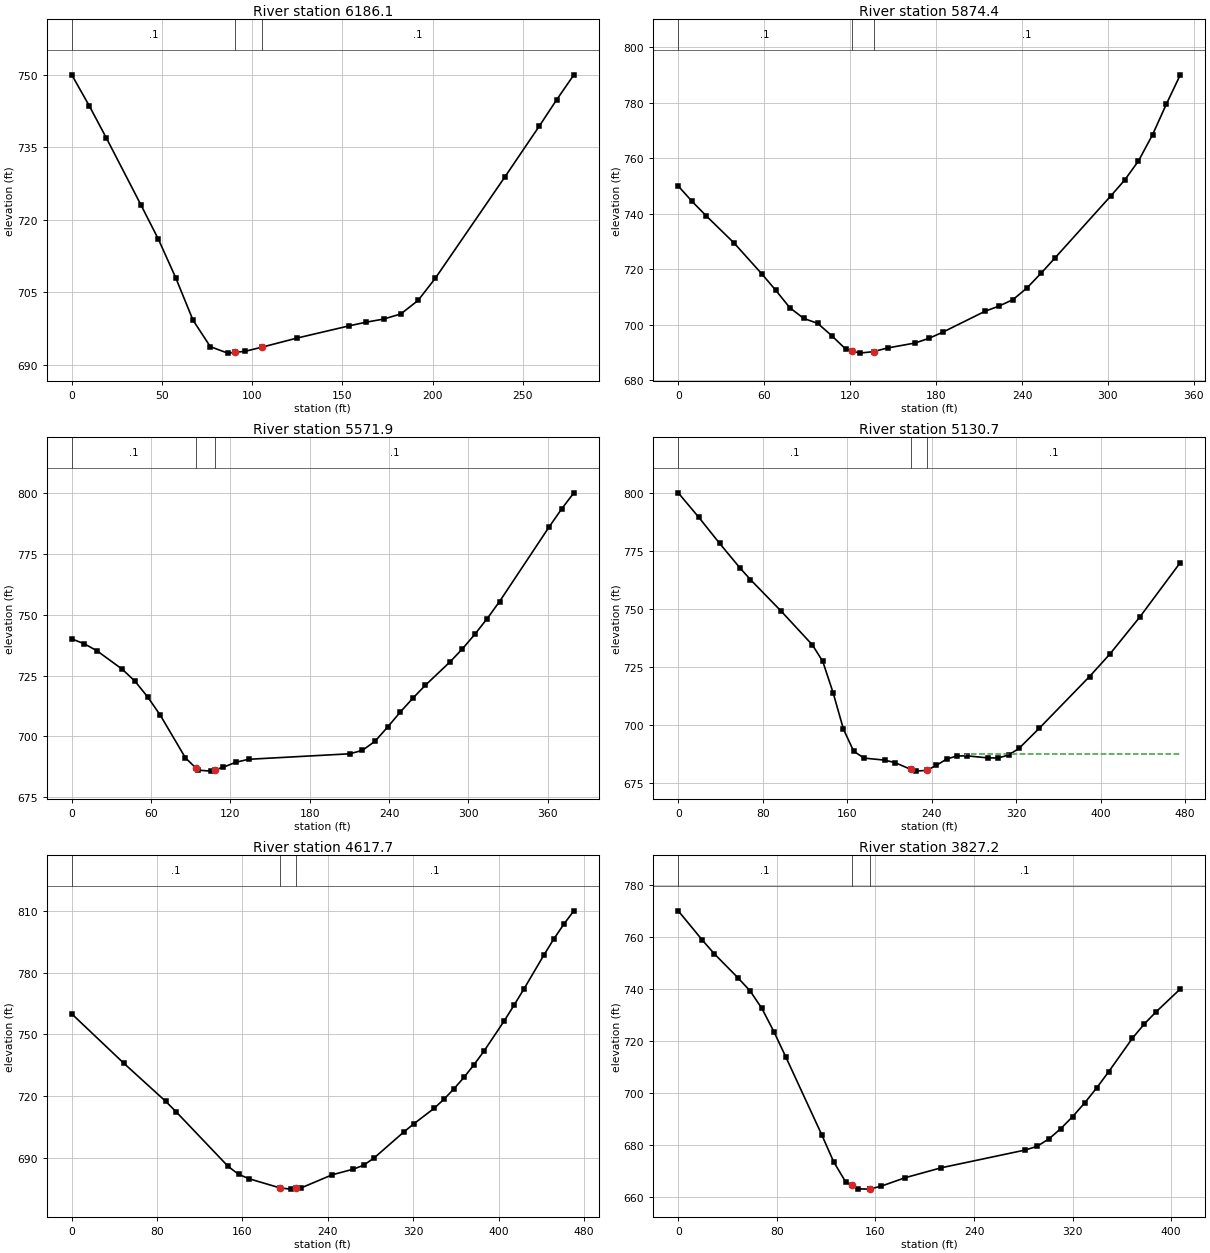
Type RM Length L Ch R = 1 ,6186.1  ,312.1,311.6,311.1
XS GIS Cut Line= 2
     1516339.802      324286.008     1516367.566      324562.961
#Sta/Elev= 23
       0  750.01     9.6  743.66    19.2  736.92    38.4  723.04      48     716
    57.6  708.04    67.2  699.24    76.8  693.76    86.4  692.42    90.7  692.59
      96  692.79   105.7  693.68   124.8  695.53   153.6  698.05   163.2  698.83
   172.8  699.46   182.4  700.53     192  703.34   201.6  707.96     240  728.84
   259.2  739.43   268.7  744.81   278.3     750
#Mann= 3 , 0 , 0
       0      .1       0    90.7    .045       0   105.7      .1       0
Bank Sta=90.7,105.7
XS Rating Curve= 0 ,0
Exp/Cntr=0.3,0.1

Type RM Length L Ch R = 1 ,5874.4  ,297.4,302.5,307.4
XS GIS Cut Line= 2
     1516033.879      324334.415     1516076.675      324682.328
#Sta/Elev= 30
       0     750     9.7  744.42    19.5  739.27      39  729.46    58.4  718.32
    68.2  712.38    77.9  706.16    87.6  702.32    97.4  700.52   107.1  696.12
   116.8  691.32   121.4  690.62   126.6  689.82   136.4  690.37   146.1  691.67
   165.5  693.48   175.3   695.2     185  697.44   214.2   704.9     224  706.78
   233.7  709.09   243.4  713.26   253.2  718.54   262.9  724.03   301.8  746.32
   311.6   752.1   321.3  759.03   331.1  768.44   340.8  779.53   350.5  790.03
#Mann= 3 , 0 , 0
       0      .1       0   121.4    .045       0   136.4      .1       0
Bank Sta=121.4,136.4
XS Rating Curve= 0 ,0
Exp/Cntr=0.3,0.1

Type RM Length L Ch R = 1 ,5571.9  ,440.7,441.2,441.5
XS GIS Cut Line= 3
     1515759.073      324354.884     1515734.661       324602.19
     1515682.869      324722.879
#Sta/Elev= 30
       0  740.03     9.6     738    19.1  735.13    38.2  727.57    47.8  722.66
    57.4  716.22    66.9  708.75      86  691.17    93.6  687.19    95.6  686.14
   105.1  685.74   108.6  686.33   114.7  687.36   124.2   689.4   133.8   690.6
   210.3  692.86   219.8  694.26   229.4     698     239  703.88   248.5  709.99
   257.9  715.62   267.3  720.91     286  730.52   295.4  735.88   304.8  741.87
   314.2  748.34   323.6  755.39   361.1  786.02   370.5  793.35   379.8  800.02
#Mann= 3 , 0 , 0
       0      .1       0    93.6    .045       0   108.6      .1       0
Bank Sta=93.6,108.6
XS Rating Curve= 0 ,0
Exp/Cntr=0.3,0.1

Type RM Length L Ch R = 1 ,5130.7  ,496,513,530
XS GIS Cut Line= 3
     1515338.349      324215.347     1515300.205      324535.779
     1515353.789      324678.982
#Sta/Elev= 30
       0     800    19.6  789.39    39.1   778.3    58.7  767.56    68.4  762.66
    97.8  748.94   127.1  734.54   136.9  727.47   146.7     714   156.5   698.3
   166.2  688.81     176  685.86   195.6  684.98   205.4   683.9   220.2  681.03
   224.9  680.25   235.2  680.57   244.5  682.72   254.2  685.43     264  686.78
   273.8  686.82   293.4  685.94   303.1  685.92   312.9  687.18   322.7  689.99
   341.8  698.61   389.6  720.95   408.7  730.52   437.4  746.65   475.6     770
#Mann= 3 , 0 , 0
       0      .1       0   220.2    .045       0   235.2      .1       0
#XS Ineff= 2 , 0
                          271.83           687.7
Permanent Ineff=
       F       F
Bank Sta=220.2,235.2
XS Rating Curve= 0 ,0
Exp/Cntr=0.3,0.1

Type RM Length L Ch R = 1 ,4617.7  ,810.3,790.6,770.8
XS GIS Cut Line= 3
     1515004.972       324107.08     1514788.753      324290.074
     1514682.139      324444.084
#Sta/Elev= 30
       0     760    48.8  736.02    87.9  717.61    97.7  712.52   146.5  685.98
   156.3  682.13     166  679.99   195.3  675.49   205.1  674.92   210.3  675.23
   214.9   675.5   244.2   681.9   263.7  684.57   273.5  686.52   283.3  690.01
   311.4  702.75   320.7  706.66   339.5  714.09   348.8  718.52   358.2  723.61
   367.6  729.15   376.9  735.26   386.3  741.86     405  756.32   414.4  764.09
   423.8  772.07   442.5  788.54   451.8  796.33   461.2  803.54   470.6  810.03
#Mann= 3 , 0 , 0
       0      .1       0   195.3    .045       0   210.3      .1       0
Bank Sta=195.3,210.3
XS Rating Curve= 0 ,0
Exp/Cntr=0.3,0.1

Type RM Length L Ch R = 1 ,3827.2  ,442.8,453.7,464.7
XS GIS Cut Line= 2
     1514161.538       323842.64     1514153.004       324249.91
#Sta/Elev= 30
       0     770    19.4  758.84    29.1  753.57    48.5  744.25    58.2   739.3
    67.9  732.49    77.6   723.6    87.3  713.86   116.4  684.02   126.1   673.6
   135.8  665.89   140.7  664.53   145.5  663.19   155.2  663.09   155.7  663.15
   164.9  664.26   184.3   667.5   213.4  671.29   281.3  678.09     291  679.49
   300.7  682.35   310.4  686.32   320.1  690.98   329.8  696.21   339.5  701.95
   349.2  708.14   368.6   721.1   378.3   726.6     388  731.31   407.4     740
#Mann= 3 , 0 , 0
       0      .1       0   140.7    .045       0   155.7      .1       0
Bank Sta=140.7,155.7
XS Rating Curve= 0 ,0
Exp/Cntr=0.3,0.1

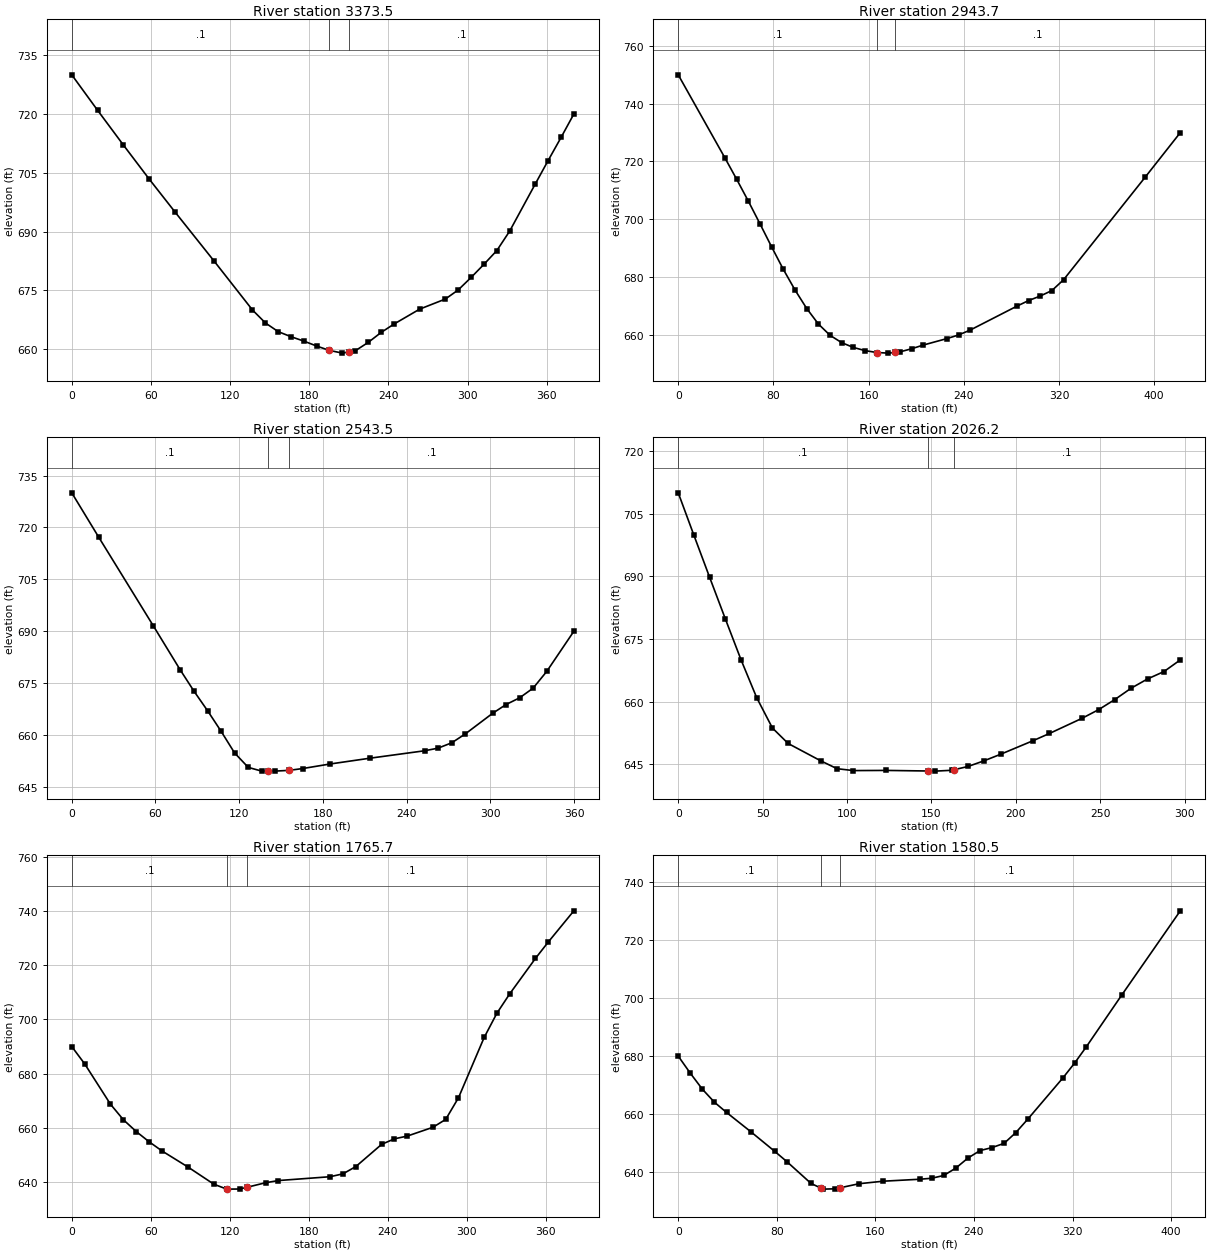
Type RM Length L Ch R = 1 ,3373.5  ,436.4,429.8,423
XS GIS Cut Line= 3
     1513827.826      323811.429     1513739.619      323916.287
     1513621.509      324129.323
#Sta/Elev= 30
       0     730    19.6  720.94    39.2  712.06    58.7   703.4    78.3  694.99
   107.7  682.57     137     670   146.8   666.7   156.5  664.48   166.2  663.19
     176  662.06   185.7   660.8   195.1  659.71   205.2     659   210.1  659.31
     215  659.62   224.7  661.73   234.5  664.27   244.2   666.4   263.7  670.22
   283.2   672.8   292.9  675.11   302.7   678.3   312.4  681.64   322.2  685.16
   331.9   690.1   351.4  702.18   361.1  708.13   370.9  714.02   380.6     720
#Mann= 3 , 0 , 0
       0      .1       0   195.1    .045       0   210.1      .1       0
Bank Sta=195.1,210.1
XS Rating Curve= 0 ,0
Exp/Cntr=0.3,0.1

Type RM Length L Ch R = 1 ,2943.7  ,399.1,400.2,401.2
XS GIS Cut Line= 2
     1513395.864      323566.475     1513307.286      323979.127
#Sta/Elev= 30
       0     750    39.3   721.2    49.1  713.86    58.9  706.29    68.7  698.44
    78.5  690.44    88.3  682.68    98.2  675.49     108  669.11   117.8  663.74
   127.6  659.84   137.4  657.29   147.2  655.64     157  654.54     167  653.88
   176.7  653.67     182  653.91   186.5  654.12   196.3   655.2   206.1  656.48
   225.8   658.7   235.6  659.95   245.4  661.65   284.6  669.92   294.4  671.85
   304.3  673.44   314.1  675.34   323.9  679.08   392.6  714.64     422     730
#Mann= 3 , 0 , 0
       0      .1       0     167    .045       0     182      .1       0
Bank Sta=167,182
XS Rating Curve= 0 ,0
Exp/Cntr=0.3,0.1

Type RM Length L Ch R = 1 ,2543.5  ,525.6,517.3,509
XS GIS Cut Line= 2
     1513014.519      323493.599     1512923.059        323841.7
#Sta/Elev= 26
       0     730    19.4  717.13    58.4  691.61    77.8  678.81    87.6   672.7
    97.3  667.08     107  661.14   116.7  654.86   126.5  650.68   136.2   649.6
   140.8   649.6   145.9  649.61   155.8  649.82   165.4  650.34   184.8  651.64
     214  653.35   252.9  655.48   262.6  656.24   272.4  657.79   282.1  660.35
   301.6  666.28   311.3  668.84     321  670.77   330.7  673.57   340.5  678.42
   359.9     690
#Mann= 3 , 0 , 0
       0      .1       0   140.8    .045       0   155.8      .1       0
Bank Sta=140.8,155.8
XS Rating Curve= 0 ,0
Exp/Cntr=0.3,0.1

Type RM Length L Ch R = 1 ,2026.2  ,262.1,260.6,258.9
XS GIS Cut Line= 3
     1512437.605      323494.041     1512459.526      323555.332
     1512485.793      323786.105
#Sta/Elev= 28
       0  710.01     9.3  699.83    18.6  689.77    27.9  679.82    37.2  670.02
    46.5  660.93    55.8  653.68    65.1  649.98    84.4  645.83    94.1  643.94
   103.8  643.49   123.2  643.53   148.1  643.39   152.2  643.36   161.9  643.56
   163.1  643.67   171.6  644.47   181.2  645.84   190.9  647.39   210.3  650.67
   219.9  652.38   239.3  656.03     249  658.08   258.6   660.5   268.3  663.23
     278  665.44   287.7   667.2   297.4     670
#Mann= 3 , 0 , 0
       0      .1       0   148.1    .045       0   163.1      .1       0
Bank Sta=148.1,163.1
XS Rating Curve= 0 ,0
Exp/Cntr=0.3,0.1

Type RM Length L Ch R = 1 ,1765.7  ,184.5,185.2,186
XS GIS Cut Line= 3
     1512194.346      323572.506     1512235.799      323794.203
     1512282.929      323942.561
#Sta/Elev= 30
       0     690     9.8  683.62    29.4  668.75    39.2  663.03      49  658.67
    58.8   654.9    68.6  651.52    88.2  645.63   107.9  639.29   117.7  637.48
   117.8  637.48   127.5  637.52   132.8  638.13   147.1  639.83   156.9  640.64
   196.1  642.05   205.9  643.11   215.7   645.8   235.3  653.99     245  656.01
   254.7  657.02   274.2  660.26   283.9  663.16   293.6  671.13   313.1  693.34
   322.8   702.3   332.6  709.48     352  722.44   361.8  728.52   381.2     740
#Mann= 3 , 0 , 0
       0      .1       0   117.8    .045       0   132.8      .1       0
Bank Sta=117.8,132.8
XS Rating Curve= 0 ,0
Exp/Cntr=0.3,0.1

Type RM Length L Ch R = 1 ,1580.5  ,248.7,248.7,248.6
XS GIS Cut Line= 3
     1512017.181      323609.765     1512056.949      323871.258
     1512115.606      324001.665
#Sta/Elev= 30
       0     680     9.8  674.12    19.6  668.61    29.4  664.13    39.2  660.62
    58.8  654.02    78.4   647.2    88.2  643.68   107.8  636.18   116.1  634.53
   117.6  634.23   127.4  634.34   131.1  634.67   146.9   636.1   166.5  636.96
   195.9  637.63   205.7  637.97   215.5  638.93   225.3  641.47   235.1  644.91
   244.9  647.49   254.7  648.53   264.5  649.99     274  653.69   283.6  658.26
   312.2   672.5   321.7   677.6   331.2   683.2   359.8  700.92   407.5     730
#Mann= 3 , 0 , 0
       0      .1       0   116.1    .045       0   131.1      .1       0
Bank Sta=116.1,131.1
XS Rating Curve= 0 ,0
Exp/Cntr=0.3,0.1

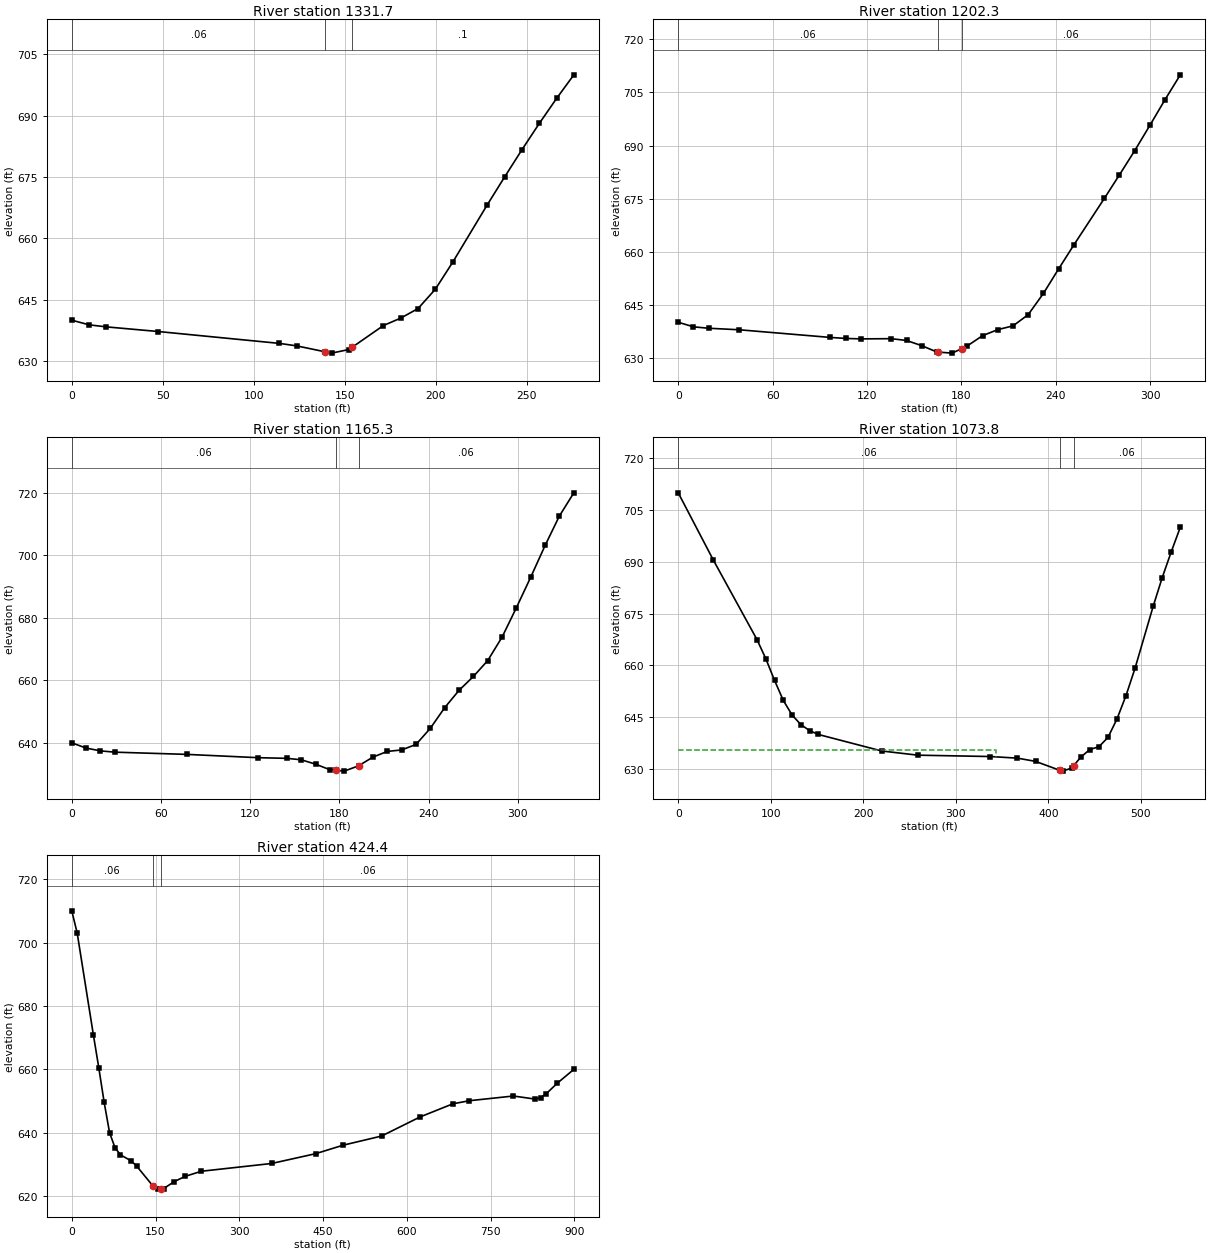
Type RM Length L Ch R = 1 ,1331.7  ,125.7,129.4,133.1
XS GIS Cut Line= 2
     1511820.331      323725.896     1511859.701      323998.876
#Sta/Elev= 21
       0     640     9.5  638.86      19  638.36    47.6  637.22   114.1  634.32
   123.6  633.71   139.2  632.26   142.7  631.94   152.2  632.82   154.2  633.43
   171.2  638.69   180.7   640.5   190.2  642.84   199.7  647.56   209.2  654.13
   228.2  668.18   237.8  675.04   247.3  681.69   256.8   688.1   266.3  694.22
   275.8     700
#Mann= 3 , 0 , 0
       0     .06       0   139.2    .045       0   154.2      .1       0
Bank Sta=139.2,154.2
XS Rating Curve= 0 ,0
Exp/Cntr=0.3,0.1

Type RM Length L Ch R = 1 ,1202.3  ,37.3,37,36.7
XS GIS Cut Line= 2
     1511716.152      323709.291     1511709.225       324028.34
#Sta/Elev= 28
       0  639.99     9.7  638.69    19.3  638.29    38.7  637.86    96.7  635.69
   106.4  635.41     116  635.28   135.4  635.34   145.1  634.83   154.7  633.37
   164.4  631.57   165.1  631.55   174.1  631.25   180.1  632.52   183.7  633.29
   193.4  636.19   203.1   637.9   212.8  638.97   222.4  642.13   232.1  648.15
   241.8  655.11   251.4  661.84   270.8  675.02   280.4  681.68   290.1  688.53
   299.8  695.73   309.4  702.99   319.1     710
#Mann= 3 , 0 , 0
       0     .06       0   165.1    .045       0   180.1     .06       0
Bank Sta=165.1,180.1
XS Rating Curve= 0 ,0
Exp/Cntr=0.3,0.1

Type RM Length L Ch R = 1 ,1165.3  ,91.7,91.4,91.2
XS GIS Cut Line= 2
     1511677.073      323699.157     1511674.158      324036.718
#Sta/Elev= 28
       0  639.99     9.6  638.31    19.3  637.41    28.9     637    77.2  636.29
   125.4  635.23   144.7  635.02   154.3  634.56     164  633.15   173.6  631.37
   177.8  631.18   183.2  630.93   192.8  632.62   202.5  635.42   212.2  637.24
   221.8  637.71   231.5  639.48   241.1  644.64   250.8  651.27   260.4  656.78
   270.1  661.25   279.7  666.32   289.4  673.87     299  683.27   308.6     693
   318.3  703.18   327.9   712.6   337.6     720
#Mann= 3 , 0 , 0
       0     .06       0   177.8    .045       0   192.8     .06       0
Bank Sta=177.8,192.8
XS Rating Curve= 0 ,0
Exp/Cntr=0.3,0.1

Type RM Length L Ch R = 1 ,1073.8  ,623.9,649.4,674.9
XS GIS Cut Line= 3
     1511623.481      323480.246     1511584.111      323626.394
     1511584.966      324017.643
#Sta/Elev= 30
       0     710    37.8  690.59    85.1  667.49    94.6  661.97   104.1  655.66
   113.5  649.88     123  645.66   132.4  642.88   141.9  641.13   151.4     640
   219.8  635.22     259     634   337.2  633.61   366.6  633.14   386.1  632.21
   412.5   629.6   415.4  629.38   425.2  630.27   427.5  631.01     435  633.42
   444.8  635.64   454.6  636.44   464.4  639.14   474.1  644.45   483.9  651.26
   493.7  659.21   513.3  677.16     523   685.4   532.8  692.92   542.6  700.04
#Mann= 3 , 0 , 0
       0     .06       0   412.5    .045       0   427.5     .06       0
#XS Ineff= 2 , 0
          343.94  635.57
Permanent Ineff=
       F       F
Bank Sta=412.5,427.5
XS Rating Curve= 0 ,0
Exp/Cntr=0.3,0.1

Type RM Length L Ch R = 1 ,424.4   ,430,424.4,418.9
XS GIS Cut Line= 3
     1511377.419      323404.368     1511076.817        323580.1
     1511030.531      324129.165
#Sta/Elev= 30
       0     710     9.7  702.99    38.7  670.87    48.4  660.48      58  649.61
    67.7  640.02    77.4  635.31      87  633.06   106.4  631.13   116.1  629.51
   145.1  623.28   154.8  622.22   160.1  622.31   164.4  622.38   183.8  624.62
   203.1  626.25   232.1  627.86     358  630.31   436.8   633.4     486  636.08
   554.8  638.96   623.7  644.98   682.7  649.14   712.3  650.11     791  651.59
   830.3  650.61   840.2  651.12     850  652.35   869.7  655.66   899.2  659.99
#Mann= 3 , 0 , 0
       0     .06       0   145.1    .045       0   160.1     .06       0
Bank Sta=145.1,160.1
XS Rating Curve= 0 ,0
Exp/Cntr=0.3,0.1

Chan Stop Cuts=-1
Use User Specified Reach Order=0
Composite Channel Slope=5